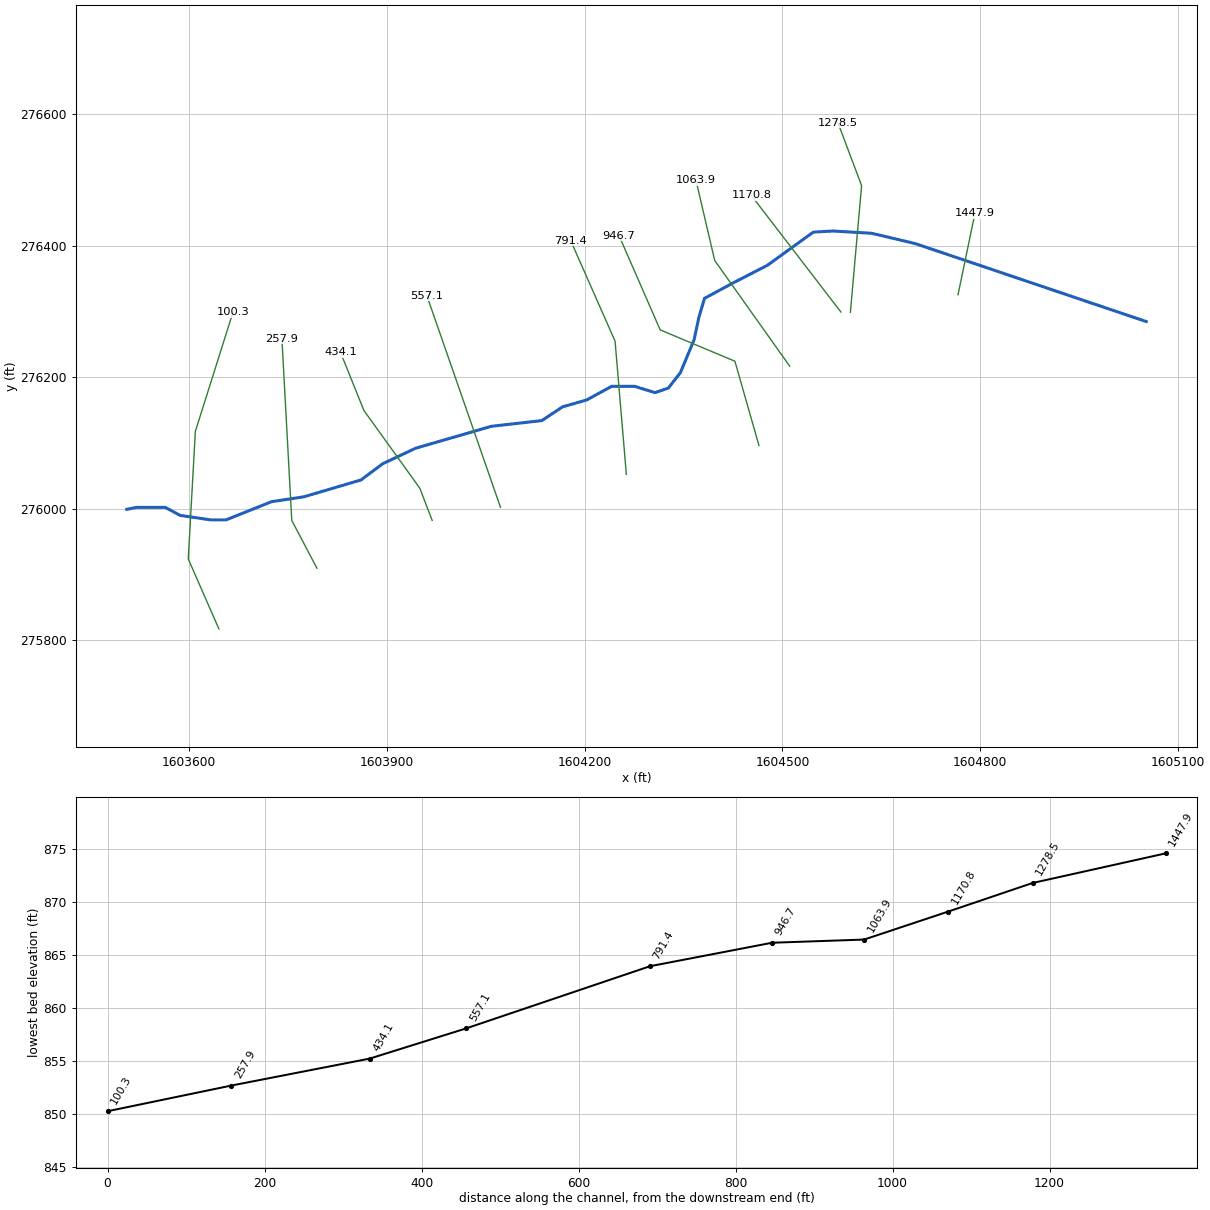
--- NP3.prj (project) ---

Proj Title=NP3
Current Plan=p01
Default Exp/Contr=0,0
English Units
Geom File=g01
Flow File=f01
Plan File=p01
BEGIN DESCRIPTION:
END DESCRIPTION:
DSS Export Rating Curves= 0
DSS Export Rating Curve Sorted= 0
DSS Export Volume Flow Curves= 0
DXF OffsetX= 0
DXF OffsetY= 0
DXF ScaleX= 0
DXF ScaleY= 0

--- NP3.p01 (plan) ---

Plan Title=Floodplain
Program Version=4.00
Geom File=g01
Flow File=f01
K Sum by GR=0
Std Step Tol=0.01
Critical Tol=0.01
Num of Std Step Trials=20
Max Error Tol=0.3
Flow Tol Ratio=0.001
Split Flow NTrial=30
Split Flow Tol=0.02
Split Flow Ratio=0.02
Log Output Level=0
Friction Slope Method=1
Unsteady Friction Slope Method=2
Unsteady Bridges Friction Slope Method=1
Global Log Level=0
CheckData=False
Run HTab=0
Run UNet=0
Run PostProcess=0
UNET Theta=0
UNET Theta Warmup=0
UNET ZTol=0
UNET ZSATol=0
UNET MxIter=0
UNET MaxInSteps=0
UNET DtIC=0
UNET DtMin=0
UNET MaxCRTS=0
UNET WFStab=0
UNET SFStab=0
UNET WFX=0
UNET SFX=0
UNET DSS MLevel=0
UNET DZMax Abort=0
UNET Convert EG Bridges=0
UNET Use Existing IB Tables=0
UNET Froude Limit=0
UNET Froude Power=0
Write IC File=0
Echo Input=False
Echo Output=False
Write Detailed=0

--- NP3.f01 (steady flow) ---

Flow Title=NFF Regression Equation
Program Version=4.10
Number of Profiles= 1
Profile Names=P100yr
River Rch & RM=NP3,Main            ,1447.9
382.6939
River Rch & RM=NP3,Main            ,557.1
395.8803
River Rch & RM=NP3,Main            ,257.9
400.0246
Boundary for River Rch & Prof#=NP3,Main            , 1
Up Type= 0
Dn Type= 3
Dn Slope=0.01534
DSS Import GetInterval= 0
DSS Import GetPeak= 0
DSS Import FillOption= 0

--- NP3.g01 (geometry) ---

Geom Title=USGS 10m DEM
Program Version=4.10

River Reach=NP3             ,Main
Reach XY= 30
     1605051.619      276284.628     1604701.293        276403.2
     1604635.321      276418.825     1604576.293      276422.298
     1604546.779      276420.562     1604477.335      276370.214
     1604423.515      276342.436     1604381.849      276319.867
     1604373.168      276290.353     1604366.224      276257.367
      1604345.39       276207.02     1604327.168      276183.623
     1604306.856      276176.591     1604275.946      276186.186
     1604241.223      276186.186     1604203.029      276165.353
     1604166.571      276154.937     1604135.321      276134.103
     1604058.932      276125.423     1603944.168      276092.164
     1603894.168      276068.553     1603861.015      276043.826
     1603774.377      276018.206     1603725.599      276010.839
     1603656.328      275983.062     1603633.758      275983.062
     1603586.883      275990.006     1603564.314      276002.159
     1603520.911      276002.159     1603505.986      275999.263

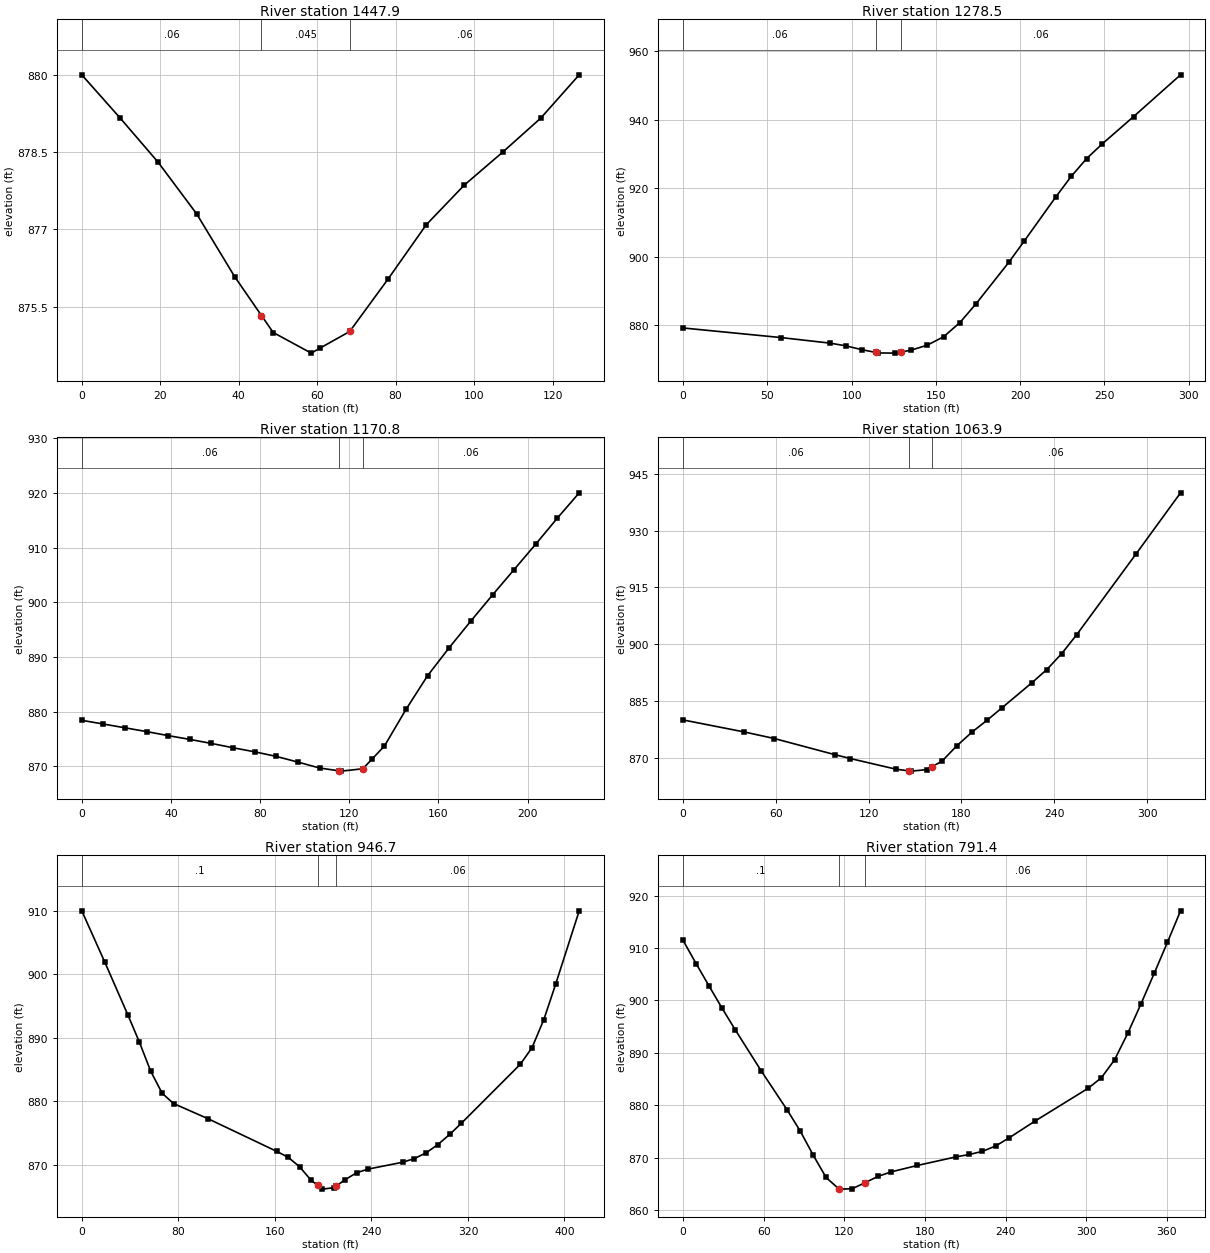
Type RM Length L Ch R = 1 ,1447.9  ,166.8,169.4,172
XS GIS Cut Line= 2
     1604766.225      276325.413     1604791.968       276449.58
#Sta/Elev= 16
       0     880     9.8  879.16    19.5   878.3    29.3   877.3      39  876.08
    45.8  875.33    48.8     875    58.5   874.6    60.8   874.7    68.3  875.02
      78  876.03    87.8  877.09    97.5  877.86   107.3   878.5     117  879.16
   126.8     880
#Mann= 3 , 0 , 0
       0     .06       0    45.8    .045       0    68.3     .06       0
Bank Sta=45.8,68.3
XS Rating Curve= 0 ,0
Exp/Cntr=0.3,0.1

Type RM Length L Ch R = 1 ,1278.5  ,90.7,107.7,124.8
XS GIS Cut Line= 3
     1604603.043      276298.824     1604620.039      276491.262
     1604584.232      276586.748
#Sta/Elev= 22
       0  879.16      58  876.36    86.9  874.75    96.6  873.94   106.2   872.8
   114.2  872.03   115.9  871.87   125.6  871.81   129.2  872.13   135.2  872.66
   144.9  874.14   154.6   876.6   164.2   880.7   173.9  886.27   193.2   898.3
   202.5   904.6     221  917.34   230.3  923.44   239.5  928.68   248.8  932.98
   267.4  940.95   295.2  953.13
#Mann= 3 , 0 , 0
       0     .06       0   114.2    .045       0   129.2     .06       0
Bank Sta=114.2,129.2
XS Rating Curve= 0 ,0
Exp/Cntr=0.3,0.1

Type RM Length L Ch R = 1 ,1170.8  ,107.6,106.8,105.9
XS GIS Cut Line= 2
     1604588.572      276299.204     1604452.842      276476.329
#Sta/Elev= 26
       0   878.4     9.7  877.72    19.4  877.03    29.1  876.34    38.8   875.6
    48.5  874.91    58.2  874.17    67.9  873.38    77.6  872.64    87.3   871.8
      97  870.76   106.7  869.68   115.3  869.17   116.4  869.11   126.1  869.54
   130.3  871.34   135.8   873.7   145.5  880.41   155.2  886.58   164.9   891.7
   174.6  896.57   184.3  901.32     194  905.97   203.8  910.67   213.4  915.38
   223.2     920
#Mann= 3 , 0 , 0
       0     .06       0   115.3    .045       0   126.1     .06       0
Bank Sta=115.3,126.1
XS Rating Curve= 0 ,0
Exp/Cntr=0.3,0.1

Type RM Length L Ch R = 1 ,1063.9  ,103.5,117.2,130.9
XS GIS Cut Line= 3
     1604511.072       276216.81     1604397.341       276377.43
     1604369.038      276499.085
#Sta/Elev= 21
       0     880    39.4  876.84      59  875.09    98.4   870.8   108.2   869.8
   137.8  866.98   145.8  866.57   147.6  866.48   157.4  866.87   160.8  867.63
   167.3  869.07   177.1  873.21     187  876.85   196.8     880   206.4  883.27
   225.6  889.84   235.2  893.31   244.8  897.51   254.5   902.5   292.9  923.85
   321.7     940
#Mann= 3 , 0 , 0
       0     .06       0   145.8    .045       0   160.8     .06       0
Bank Sta=145.8,160.8
XS Rating Curve= 0 ,0
Exp/Cntr=0.3,0.1

Type RM Length L Ch R = 1 ,946.7   ,180.7,155.4,130
XS GIS Cut Line= 4
     1604464.435      276096.221     1604427.982      276224.335
     1604314.705      276271.979     1604252.369      276415.055
#Sta/Elev= 30
       0     910      19  901.95    38.1  893.65    47.6  889.39    57.1  884.75
    66.6  881.27    76.1  879.65   104.7  877.26   161.6  872.12     171   871.2
   180.5   869.7   189.9   867.6   195.4  866.78   199.4  866.18   208.8   866.4
   210.4  866.61   218.3  867.67   227.7  868.76   237.2  869.33   265.8  870.41
   275.6  870.99   285.4   871.9   295.1   873.2   304.9   874.8   314.6  876.56
   363.4  885.84   373.1  888.45   382.9  892.88   392.6   898.4   412.2     910
#Mann= 3 , 0 , 0
       0      .1       0   195.4    .045       0   210.4     .06       0
Bank Sta=195.4,210.4
XS Rating Curve= 0 ,0
Exp/Cntr=0.3,0.1

Type RM Length L Ch R = 1 ,791.4   ,228.6,234.2,239.9
XS GIS Cut Line= 3
     1604263.386      276052.358     1604246.297       276254.83
     1604178.983      276407.696
#Sta/Elev= 30
       0  911.42     9.7  906.99    19.4  902.69      29  898.49    38.7  894.41
      58  886.58    77.4  879.09    87.1  875.08    96.8  870.46   106.4  866.19
   116.1  863.97   125.8  864.04   135.5  865.21   145.1  866.41   154.8  867.26
   174.2  868.48   203.2  870.13     213  870.58   222.8  871.18   232.7  872.22
   242.5  873.74   262.1  876.99   301.4  883.21   311.3  885.23   321.1  888.65
   330.9   893.7   340.8  899.35   350.6  905.15   360.4  911.05   370.2  917.08
#Mann= 3 , 0 , 0
       0      .1       0   116.1    .045       0   135.5     .06       0
Bank Sta=116.1,135.5
XS Rating Curve= 0 ,0
Exp/Cntr=0.3,0.1

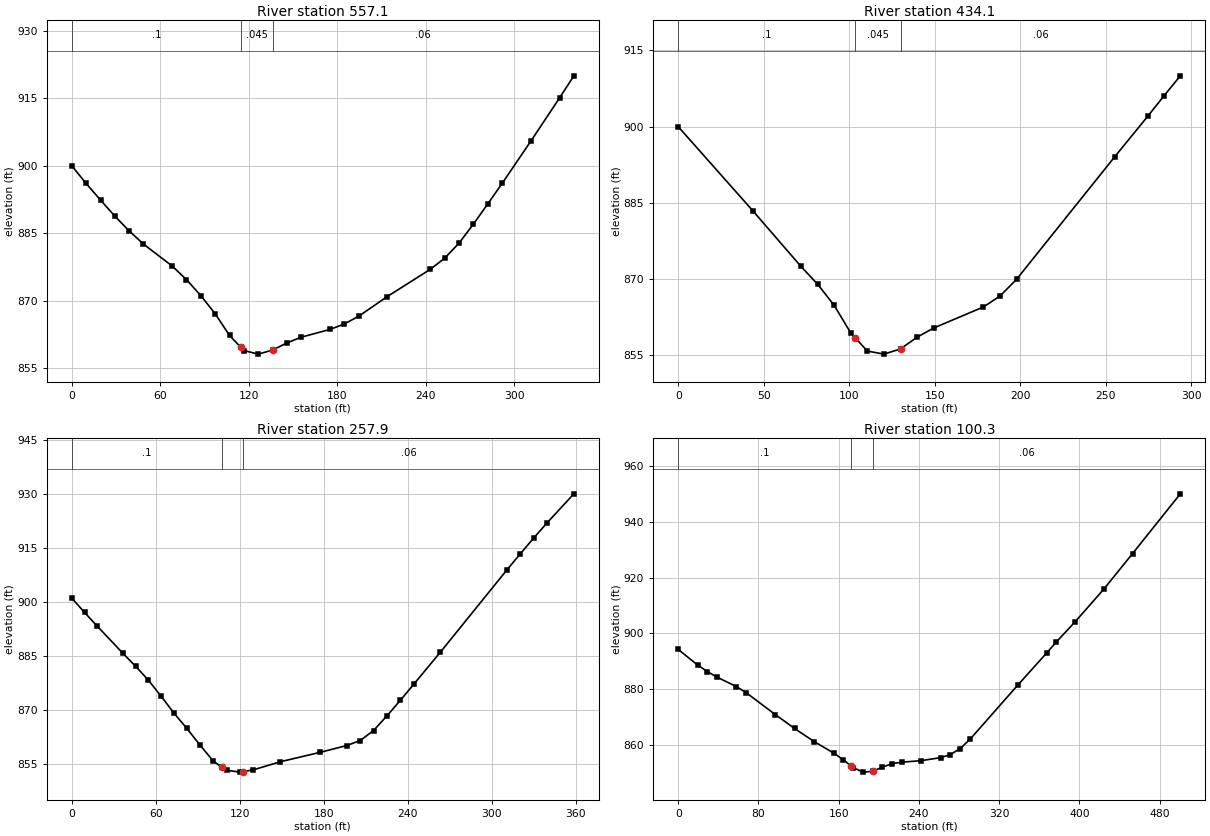
Type RM Length L Ch R = 1 ,557.1   ,116.5,123,129.5
XS GIS Cut Line= 2
     1604072.542      276002.372     1603960.916      276324.058
#Sta/Elev= 30
       0     900     9.7  896.08    19.5  892.36    29.2   888.8    38.9  885.52
    48.6  882.59    68.1   877.7    77.8  874.68    87.6  871.09    97.3  867.06
     107  862.27   114.6  859.64   116.7  858.91   126.5  858.11   136.2  859.02
   145.9   860.6   155.7  861.89   175.1   863.6   184.8  864.81   194.6  866.54
     214  870.92   243.2  876.99   252.9  879.44   262.7  882.82   272.4  887.03
   282.1  891.51   291.9  896.09   311.3  905.46   330.8  915.08   340.5     920
#Mann= 3 , 0 , 0
       0      .1       0   114.6    .045       0   136.2     .06       0
Bank Sta=114.6,136.2
XS Rating Curve= 0 ,0
Exp/Cntr=0.3,0.1

Type RM Length L Ch R = 1 ,434.1   ,189.1,176.2,163.3
XS GIS Cut Line= 4
     1603968.982      275982.434     1603950.236      276031.324
     1603865.421      276149.611     1603829.786      276238.426
#Sta/Elev= 19
       0     900    43.6  883.46    71.8   872.5    81.5  869.02    91.2  864.84
   100.9  859.42   103.4   858.5   110.6  855.86   120.3  855.26     130  856.29
   139.7   858.6   149.4   860.4   178.5  864.54   188.2   866.7   197.9     870
   255.3   894.1   274.5  902.02     284  906.04   293.6     910
#Mann= 3 , 0 , 0
       0      .1       0   103.4    .045       0     130     .06       0
Bank Sta=103.4,130
XS Rating Curve= 0 ,0
Exp/Cntr=0.3,0.1

Type RM Length L Ch R = 1 ,257.9   ,160.2,157.7,155.1
XS GIS Cut Line= 3
     1603794.302      275909.664     1603756.168      275982.297
     1603741.187      276258.357
#Sta/Elev= 30
       0  901.05     9.1  897.07    18.2  893.25    36.5  885.72    45.6   882.1
    54.7  878.26    63.8  873.79    72.9  869.14      82  864.94    91.6  860.22
   101.1  855.74   107.5  854.04   110.6  853.22   120.2  852.72   122.5  852.87
   129.7  853.36   148.8  855.59   177.4  858.22   196.4  860.11     206   861.5
   215.5  864.27     225  868.32   234.6  872.66   244.1  877.08   263.2  886.03
   310.8  908.92   320.4   913.4   329.9  917.76   339.4  921.94   358.5     930
#Mann= 3 , 0 , 0
       0      .1       0   107.5    .045       0   122.5     .06       0
Bank Sta=107.5,122.5
XS Rating Curve= 0 ,0
Exp/Cntr=0.3,0.1

Type RM Length L Ch R = 1 ,100.3   ,94.6,100.3,106
XS GIS Cut Line= 4
     1603645.647      275817.433     1603599.217      275923.758
     1603609.949       276117.64      1603667.11       276299.12
#Sta/Elev= 30
       0  894.25    19.3  888.67      29  886.33    38.7  884.32      58  880.94
    67.7  878.77    96.7  870.94     116  865.93   135.4  861.26   154.9  857.15
   164.6   854.7   172.5  852.46   174.3  851.95     184   850.3   193.7  850.59
   203.4  852.06   213.1  853.33   222.8  853.86   242.2  854.41   261.6  855.49
   271.4  856.59   281.1  858.76   290.8  862.03   338.7  881.57   367.3  892.99
   376.8  896.89   395.8  904.21   424.4  915.92   452.9  928.59   500.5  949.99
#Mann= 3 , 0 , 0
       0      .1       0   172.5    .045       0   193.7     .06       0
Bank Sta=172.5,193.7
XS Rating Curve= 0 ,0
Exp/Cntr=0.3,0.1

Chan Stop Cuts=-1
Use User Specified Reach Order=0
Composite Channel Slope=5